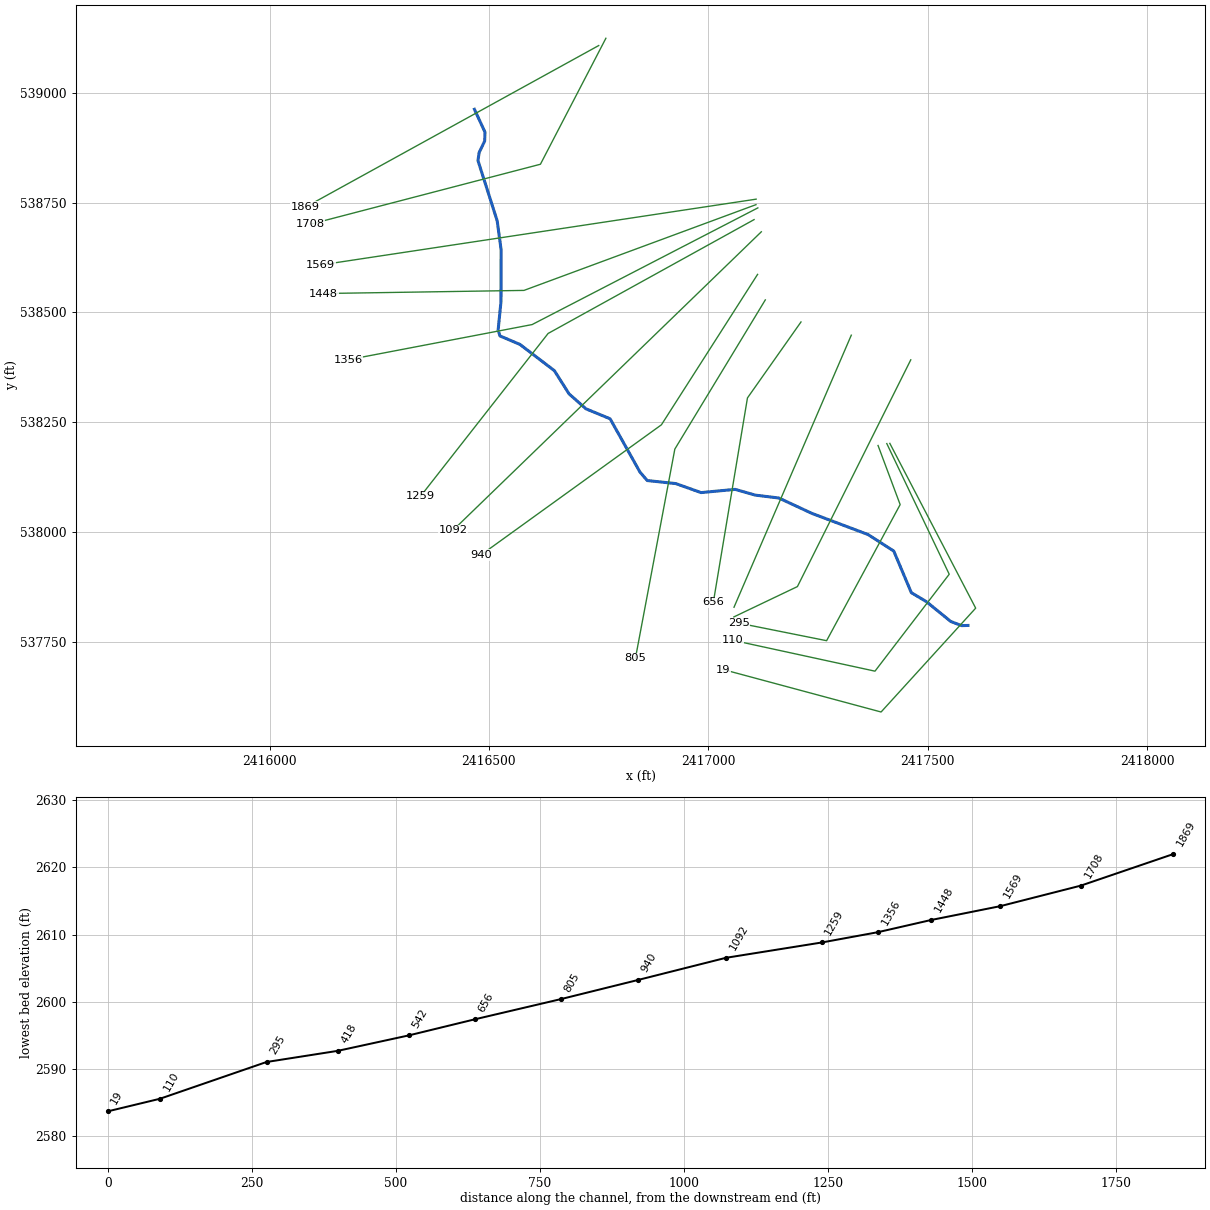
--- BLCKTHRNCK_T1.prj (project) ---

Proj Title=BLCKTHRNCK_T1
Current Plan=p01
Default Exp/Contr=0,0
English Units
Geom File=g01
Flow File=f01
Plan File=p01
BEGIN DESCRIPTION:
Stream Name: Blackthorn Creek Tributary 1
Flood Zone: Approximate
Pendleton County, West Virginia
HEC-RAS Version: 5.0.7
Hydrology Method:
Regression
Model Notes:
NA
END DESCRIPTION:
DSS Export Rating Curves= 0
DSS Export Rating Curve Sorted= 0
DSS Export Volume Flow Curves= 0
DXF OffsetX= 0
DXF OffsetY= 0
DXF ScaleX= 0
DXF ScaleY= 0

--- BLCKTHRNCK_T1.p01 (plan) ---

Plan Title=Floodplain
Program Version=5.07
Short Identifier=Floodplain
Geom File=g01
Flow File=f01
Subcritical Flow
K Sum by GR= 0
Std Step Tol= 0.01
Critical Tol= 0.01
Num of Std Step Trials= 20
Max Error Tol= 0.3
Flow Tol Ratio= 0.001
Split Flow NTrial= 30
Split Flow Tol= 0.02
Split Flow Ratio= 0.02
Log Output Level= 0
Friction Slope Method= 1
Unsteady Friction Slope Method= 2
Unsteady Bridges Friction Slope Method= 1
Parabolic Critical Depth
Global Vel Dist= 0 , 0 , 0
Global Log Level= 0
CheckData=True
Encroach Param=-1 ,0,0, 0
Mapping Interval=1HOUR
Computation Time Step Use Courant=        0
Computation Time Step Use Time Series=    0
Computation Time Step Count To Double=0
Computation Time Step Max Doubling=0
Computation Time Step Max Halving=0
Computation Time Step Residence Courant=0
Run HTab= 0
Run UNet= 0
Run Sediment= 0
Run PostProcess= 0
Run WQNet= 0
Run RASMapper= 0
UNET Theta= 0
UNET Theta Warmup= 0
UNET ZTol= 0
UNET ZSATol= 0
UNET MxIter= 0
UNET Max Iter WO Improvement= 0
UNET MaxInSteps= 0
UNET DtIC= 0
UNET DtMin= 0
UNET MaxCRTS= 0
UNET WFStab= 0
UNET SFStab= 0
UNET WFX= 1
UNET SFX= 1
UNET 1D Methodology=Finite Difference
UNET DSS MLevel= 1
UNET Pardiso=0
UNET DZMax Abort= 0
UNET Use Existing IB Tables= 0
UNET Froude Reduction=False
UNET Froude Limit= 0
UNET Froude Power= 0
UNET D1 Cores= 0
UNET D2 Coriolis=0
UNET D2 Cores= 0
UNET D2 Theta= 1
UNET D2 Theta Warmup= 1
UNET D2 Z Tol= 0.01
UNET D2 Volume Tol= 0.01
UNET D2 Max Iterations= 20
UNET D2 Equation= 0
UNET D2 RampUpFraction=0.1
UNET D2 TimeSlices= 1
UNET D2 BCVolumeCheck=0
UNET D1D2 MaxIter= 0
UNET D1D2 ZTol=0.01
UNET D1D2 QTol=0.1
UNET D1D2 MinQTol=1
Write IC File= 0
Write IC File at Fixed DateTime=0
Write IC File at Sim End=0
Echo Input=False
Echo Parameters=False
Echo Output=False
Write Detailed= 0
HDF Write Warmup=0
HDF Write Time Slices=0
HDF Flush=0
HDF Face Node Velocities=0
HDF Compression= 1
HDF Chunk Size= 1
HDF Spatial Parts= 1
HDF Use Max Rows=0
HDF Fixed Rows= 1
Calibration Method= 0
Calibration Iterations= 20
Calibration Max Change=0.05
Calibration Tolerance=0.2
Calibration Maximum=1.5
Calibration Minimum=0.5
Calibration Optimization Method= 1
WQ AD Non Conservative
WQ ULTIMATE=-1
WQ Max Comp Step=1HOUR
WQ Output Interval=15MIN
WQ Output Selected Increments= 0
WQ Output face flow=0
WQ Output face velocity=0
WQ Output face area=0
WQ Output face dispersion=0
WQ Output cell volume=0
WQ Output cell surface area=0
WQ Output cell continuity=0
WQ Output cumulative cell continuity=0
WQ Output face conc=0
WQ Output face dconc_dx=0
WQ Output face courant=0
WQ Output face peclet=0
WQ Output face adv mass=0
WQ Output face disp mass=0
WQ Output cell mass=0
WQ Output cell source sink temp=0
WQ Output nsm pathways=0
WQ Output nsm derived pathways=0
WQ Output MaxMinRange=-1
WQ Daily Max Min Mean=-1
WQ Daily Range=0
WQ Daily Time=0
WQ Create Restart=0
WQ Fixed Restart=0
WQ System Summary=0
WQ Write To DSS=0
WQ Use Fixed Temperature=0
Sorting and Armoring Iterations= 10
XS Update Threshold= 0.02
Bed Roughness Predictor= 0
Hydraulics Update Threshold= 0.02
Energy Slope Method= 1
Volume Change Method= 1
Sediment Retention Method= 0
XS Weighting Method= 0
Number of US Weighted Cross Sections= 1
Number of DS Weighted Cross Sections= 1
Upstream XS Weight=0
Main XS Weight=1
Downstream XS Weight=0
Number of DS XS's Weighted with US Boundary= 1
Upstream Boundary Weight= 1
Weight of XSs Associated with US Boundary= 0
Number of US XS's Weighted with DS Boundary= 1
Downstream Boundary Weight= 0.5
Weight of XSs Associated with DS Boundary= 0.5
Percentile Method= 0
Sediment Output Level= 3
Mass or Volume Output= 0
Output Increment Type= 1
Profile and TS Output Increment= 1
XS Output Flag= 0
XS Output Increment= 10
Write Gradation File= 0
Read Gradation Hotstart= 0
Write HDF5 File= 1
Write Binary Output= 1
Write DSS Sediment File= 0
SV Curve= 0
Specific Gage Flag= 0

--- BLCKTHRNCK_T1.f01 (steady flow) ---

Flow Title=Flows
Program Version=5.07
Number of Profiles= 6
Profile Names=P100yr,P10yr,P25yr,P50yr,P500yr,P101yr
River Rch & RM=BLCKTHRNCK_T1,Main            ,1869
     573     268     379     473     840     698
Boundary for River Rch & Prof#=BLCKTHRNCK_T1,Main            , 1
Up Type= 0
Dn Type= 3
Dn Slope=0.02044
Boundary for River Rch & Prof#=BLCKTHRNCK_T1,Main            , 2
Up Type= 0
Dn Type= 3
Dn Slope=0.02044
Boundary for River Rch & Prof#=BLCKTHRNCK_T1,Main            , 3
Up Type= 0
Dn Type= 3
Dn Slope=0.02044
Boundary for River Rch & Prof#=BLCKTHRNCK_T1,Main            , 4
Up Type= 0
Dn Type= 3
Dn Slope=0.02044
Boundary for River Rch & Prof#=BLCKTHRNCK_T1,Main            , 5
Up Type= 0
Dn Type= 3
Dn Slope=0.02044
Boundary for River Rch & Prof#=BLCKTHRNCK_T1,Main            , 6
Up Type= 0
Dn Type= 3
Dn Slope=0.02044
DSS Import GetInterval= 0
DSS Import GetPeak= 0
DSS Import FillOption= 0

--- BLCKTHRNCK_T1.g01 (geometry) ---

Geom Title=Geometry
Program Version=5.07

River Reach=BLCKTHRNCK_T1   ,Main
Reach XY= 30
     2416466.986538962.693000019     2416491.014538910.680999994
2416490.30900002538890.3460000162416477.59299999 538863.87000002
2416475.11400002538845.6879999942416518.86000001538708.575000018
2416527.82000002538642.2360000012416527.48500001538524.461999998
2416520.96900001538459.569999993     2416525.259538446.404000014
2416570.63100004      538427.1842416649.13999999538367.400000006
2416682.68600002538314.4319999962416721.22500002538280.399000019
2416776.21200004538257.7269999982416844.23900002538136.418000013
     2416860.898538117.0190000092416925.95300004538110.091000006
2416983.52700004538089.5840000212417061.28400001538096.915999994
     2417107.377538083.795000017     2417160.928538077.219000012
2417236.21900004538042.1870000062417364.17699999537994.004999995
     2417422.757537956.4210000042417462.83800003537861.597000018
2417497.37900004537841.0070000142417552.59400004537796.034000009
2417577.43700001 537786.549000012417591.90615082 537786.96409364

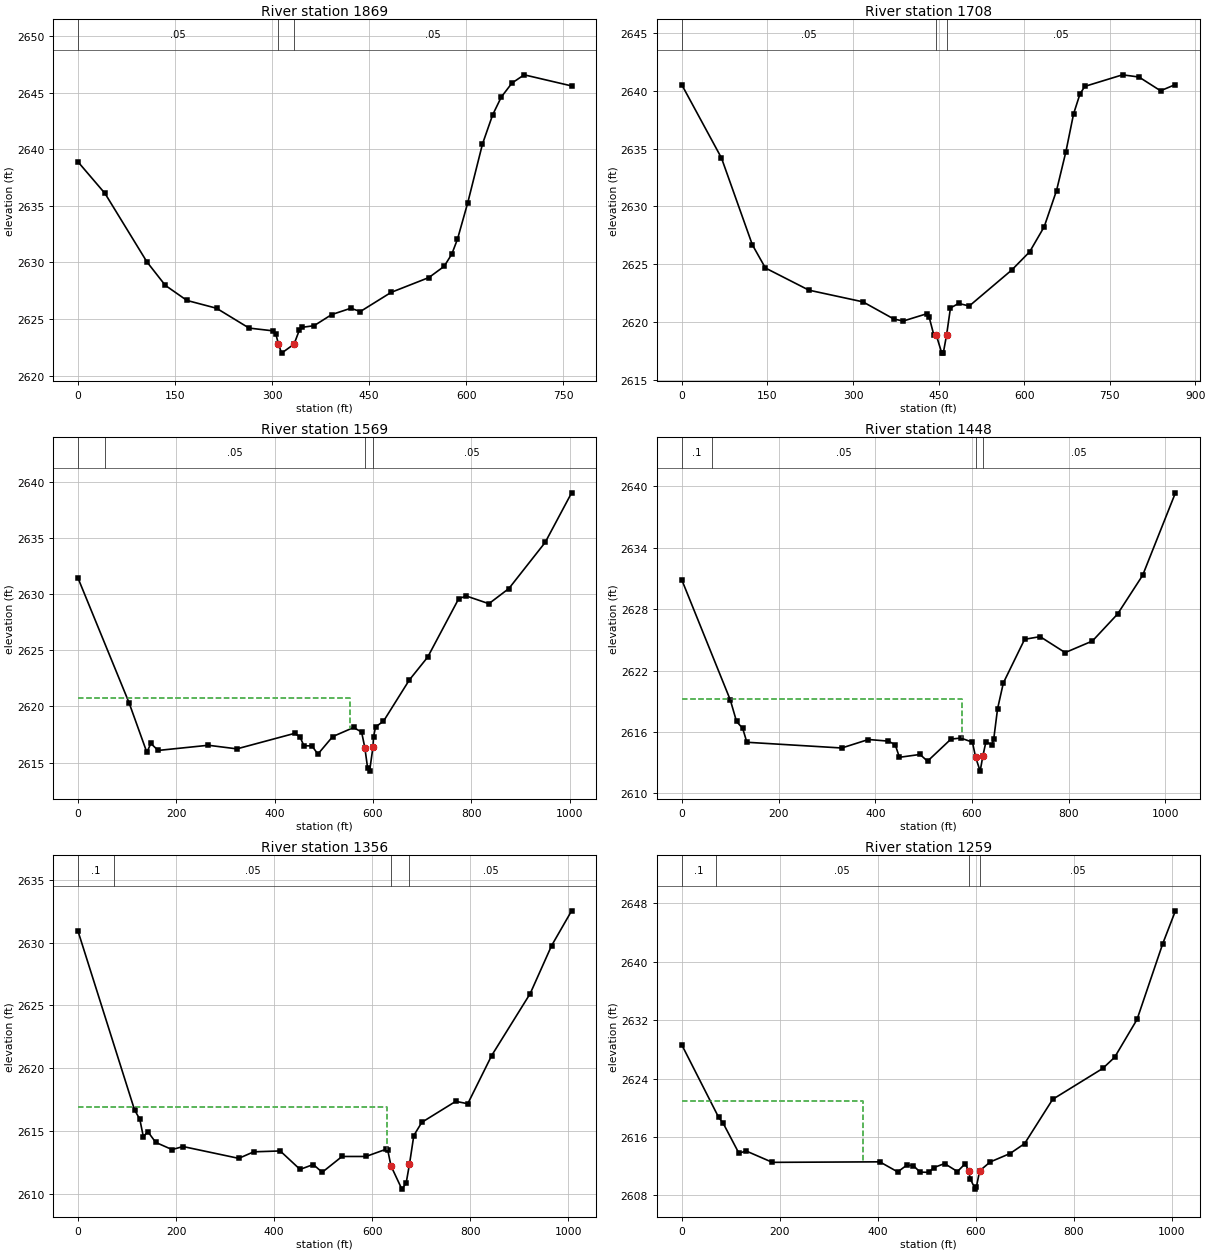
Type RM Length L Ch R = 1 ,1869    ,160.7,160.7,160.7
XS GIS Cut Line= 2
2416750.24413196539107.901756533     2416082.015      538740.005
#Sta/Elev= 30
       0 2638.87    41.6 2636.09   106.4 2630.05   134.8 2627.98   168.2 2626.65
     214 2625.96   264.3 2624.21   300.8 2623.97   305.4 2623.73   309.6 2622.82
   314.5    2622   333.8 2622.79   341.9 2624.02   346.5 2624.28   364.7 2624.42
   391.9  2625.4   421.5 2625.96   436.2 2625.67   483.8 2627.36   542.2 2628.67
   565.8 2629.66   577.6 2630.74   586.4 2632.06   602.2 2635.26     625 2640.45
   640.7 2643.02   654.1  2644.6   670.7 2645.84   689.5 2646.56   762.8 2645.58
#Mann= 3 ,-1 , 0
       0     .05       0   309.6    .045       0   333.8     .05       0
Bank Sta=309.6,333.8
XS Rating Curve= 0 ,0
Exp/Cntr=0.3,0.1

Type RM Length L Ch R = 1 ,1708    ,140.6,139.6,138.5
XS GIS Cut Line= 3
2416766.60076449 539124.49822188 2416617.3974858538837.526747444
     2416092.975      538700.869
#Sta/Elev= 30
       0 2640.51    69.4 2634.19   123.5 2626.68   146.4 2624.67   222.7 2622.75
   317.4 2621.74   371.7 2620.25   388.2 2620.08   429.5 2620.71   433.7 2620.39
   441.9 2618.84   446.1 2618.85   455.7  2617.3   458.5 2617.35  464.26 2618.91
   470.9 2621.21   485.2  2621.6   503.9 2621.38   578.3 2624.49   609.8 2626.07
   635.3 2628.24   656.9 2631.37   673.4 2634.75   686.8 2638.01     698 2639.73
   706.5 2640.39   772.6 2641.39   801.5  2641.2   839.3 2640.01   865.4 2640.55
#Mann= 3 ,-1 , 0
       0     .05       0   446.1    .045       0  464.26     .05       0
Bank Sta=446.1,464.26
XS Rating Curve= 0 ,0
Exp/Cntr=0.3,0.1

Type RM Length L Ch R = 1 ,1569    ,122,120.7,119.2
XS GIS Cut Line= 2
2417109.06985554538758.001372018     2416116.342      538608.077
#Sta/Elev= 30
       0  2631.4   103.5 2620.35   139.9 2615.92     148 2616.71   162.9 2616.09
   264.9 2616.55   323.1 2616.23   440.6 2617.61   451.4 2617.29   459.5  2616.5
   475.7  2616.5   487.8 2615.76   517.9 2617.32   560.6 2618.13   576.8 2617.72
   583.3 2616.34   588.9 2614.56     593 2614.25  599.86 2616.38   601.1  2617.3
   605.1 2618.18   621.3 2618.69   673.9 2622.36   711.2 2624.39   774.5  2629.6
   790.1 2629.82   835.7 2629.14   876.4 2630.49   950.2 2634.59    1004    2639
#Mann= 4 ,-1 , 0
       0      .1       0   54.29     .05       0   583.3    .045       0
  599.86     .05       0
#XS Ineff= 2 , 0
           553.2 2620.75
Permanent Ineff=
       F       F
Bank Sta=583.3,599.86
XS Rating Curve= 0 ,0
Exp/Cntr=0.3,0.1

Type RM Length L Ch R = 1 ,1448    ,91.2,92.2,95.8
XS GIS Cut Line= 3
 2417108.7446064538745.5004926152416579.90799432538550.159121734
      2416122.95      538543.061
#Sta/Elev= 30
       0 2630.84   100.2 2619.12     113 2617.03   125.8 2616.35   134.3    2615
   330.6 2614.44   385.9 2615.27   427.1 2615.11   441.3 2614.75   449.9 2613.53
   492.6 2613.81     508 2613.15   556.5 2615.31   576.9 2615.41   600.9 2615.01
   607.5 2613.54   616.9 2612.18   622.6 2613.68   628.9 2615.06   640.9 2614.74
   644.9 2615.28   652.9 2618.27   664.9  2620.8   708.9 2625.06   740.9 2625.32
   792.7 2623.76     849 2624.89     901 2627.52     953 2631.31  1020.8 2639.37
#Mann= 4 ,-1 , 0
       0      .1       0   61.31     .05       0   607.5    .045       0
   622.6     .05       0
#XS Ineff= 2 , 0
          578.44 2619.23
Permanent Ineff=
       F       F
Bank Sta=607.5,622.6
XS Rating Curve= 0 ,0
Exp/Cntr=0.3,0.1

Type RM Length L Ch R = 1 ,1356    ,91.7,97.3,109
XS GIS Cut Line= 3
2417112.97458006 538738.129522912416598.46751059538472.322801598
 2416178.7034309538392.054435261
#Sta/Elev= 30
       0 2630.89   115.1 2616.68   125.8 2615.94   133.1 2614.54   142.1 2614.95
   158.4 2614.09   191.6 2613.52   214.1 2613.76   327.6 2612.82   358.2 2613.34
   412.2 2613.41   452.7 2611.94   479.7 2612.33   497.8 2611.71   538.3 2612.97
     587 2612.97   627.7 2613.54   631.4 2613.49   638.2 2612.21   660.3 2610.37
     669 2610.84   675.8 2612.35   684.7 2614.64     701 2615.69   770.2 2617.36
   794.7 2617.17   843.5 2621.01     922 2625.94   965.7 2629.76  1006.5 2632.53
#Mann= 4 ,-1 , 0
       0      .1       0   73.08     .05       0   638.2    .045       0
   675.8     .05       0
#XS Ineff= 2 , 0
          629.97 2616.87
Permanent Ineff=
       F       F
Bank Sta=638.2,675.8
XS Rating Curve= 0 ,0
Exp/Cntr(USF)=0,0
Exp/Cntr=0.3,0.1

Type RM Length L Ch R = 1 ,1259    ,167.3,166.4,164.7
XS GIS Cut Line= 3
2417104.37760867538711.3996177572416634.89974517538452.063120597
     2416344.162      538081.237
#Sta/Elev= 30
       0 2628.58      75 2618.68    84.1 2617.89   116.4 2613.76   131.1 2614.07
   184.7 2612.51     404 2612.58   440.6  2611.2   458.8 2612.11   472.6 2612.06
   486.3 2611.17   504.5 2611.14   513.7 2611.78   536.3 2612.34   562.5 2611.25
   578.5 2612.33  585.63 2611.31   588.7 2610.27   598.8 2608.84   601.4  2609.2
   607.9 2611.34   629.3 2612.56     670 2613.72   699.7 2615.08     757 2621.15
   859.2 2625.38   883.5 2626.91   929.2 2632.09   981.7 2642.48  1007.6 2646.98
#Mann= 4 ,-1 , 0
       0      .1       0    69.3     .05       0  585.63    .045       0
   607.9     .05       0
#XS Ineff= 2 , 0
          369.15 2620.98
Permanent Ineff=
       F       F
Bank Sta=585.63,607.9
XS Rating Curve= 0 ,0
Exp/Cntr=0.3,0.1

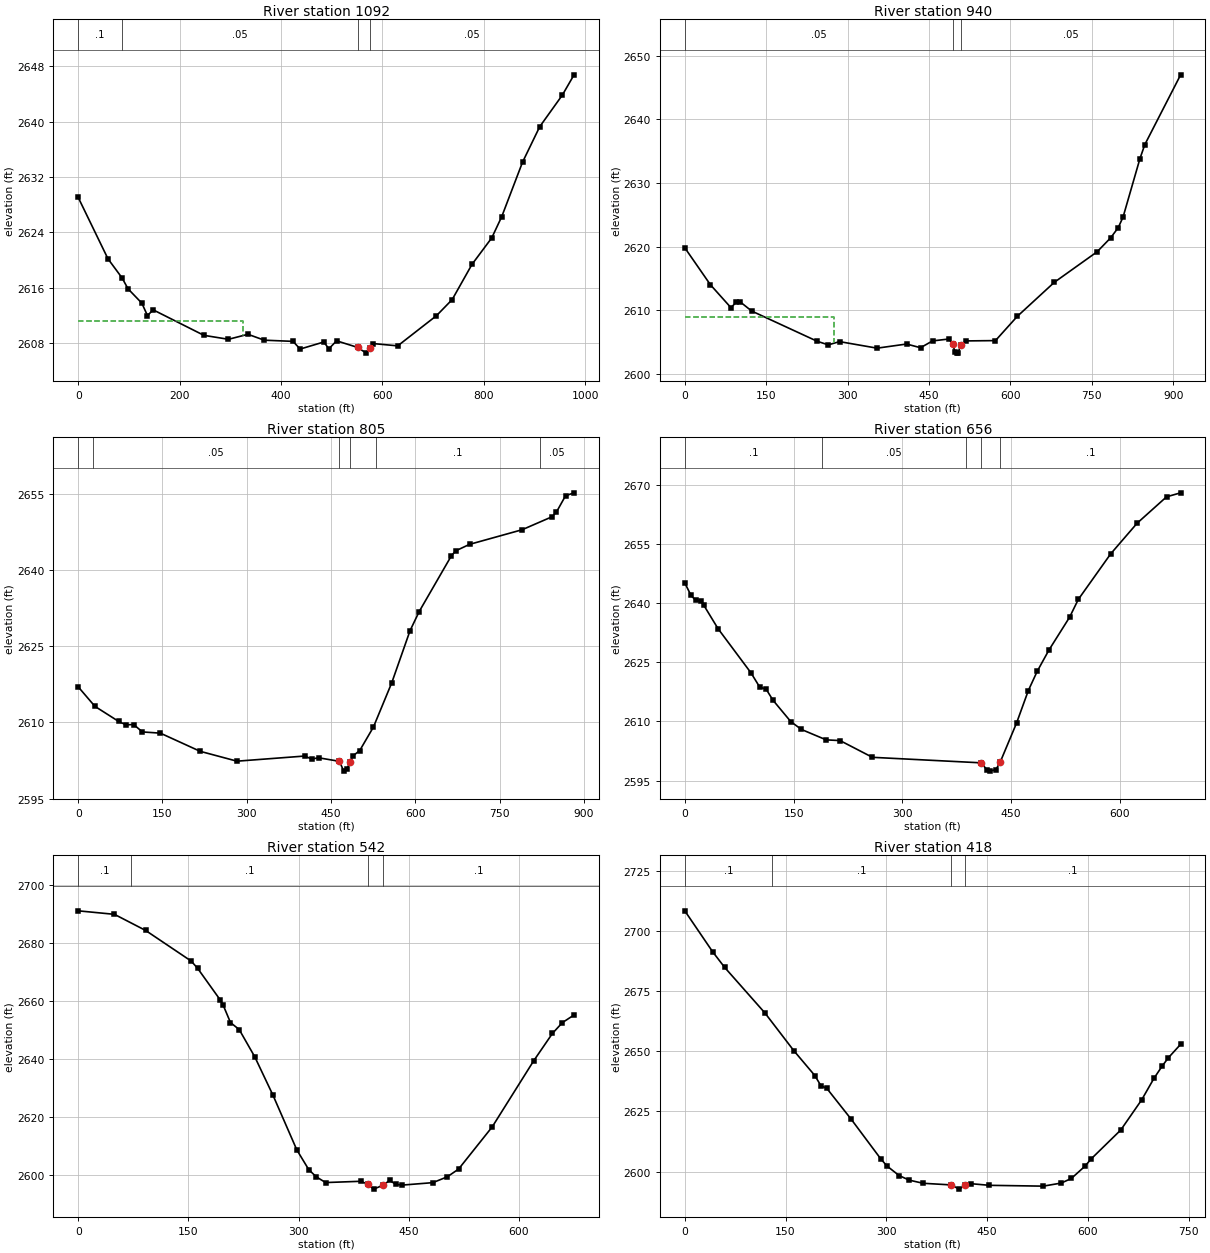
Type RM Length L Ch R = 1 ,1092    ,153.3,152.3,150.5
XS GIS Cut Line= 2
2417120.91586009538683.687242331      2416418.18      538003.795
#Sta/Elev= 30
       0 2629.06    58.7 2620.19    86.5 2617.43    98.3 2615.85   125.5 2613.78
   136.6 2611.98   147.7 2612.82   247.9 2609.13   296.3 2608.56   334.8 2609.28
     367 2608.43   423.6 2608.26   437.7 2607.15   484.4 2608.17   494.3 2607.18
   509.5 2608.34   550.9 2607.39   567.9 2606.56  574.66 2607.35   581.9 2607.94
   630.1 2607.61   706.5 2611.97   737.5  2614.3   776.6 2619.39   815.6 2623.22
   835.3  2626.3   876.2 2634.15   910.1 2639.28   954.8 2643.86   977.8 2646.78
#Mann= 4 ,-1 , 0
       0      .1       0    86.5     .05       0   550.9    .045       0
  574.66     .05       0
#XS Ineff= 2 , 0
       0   324.6 2611.19               0
Permanent Ineff=
       F       F
Bank Sta=550.9,574.66
XS Rating Curve= 0 ,0
Exp/Cntr=0.3,0.1

Type RM Length L Ch R = 1 ,940     ,126.9,134.6,141.9
XS GIS Cut Line= 3
2417112.35562117538586.648744035 2416893.1763652538244.012121734
     2416481.913      537947.566
#Sta/Elev= 30
       0 2619.83    47.2 2614.02      85 2610.42    94.7 2611.26   102.3 2611.31
   123.2 2609.89   244.3 2605.12   264.5 2604.57   285.1 2605.08   354.3 2604.05
   408.7  2604.7   434.4 2604.12   456.5 2605.19   486.7 2605.49   493.6 2604.69
   498.1 2603.42     501 2603.27   503.4  2603.3   508.4 2604.53   518.2 2605.19
   572.5 2605.24   612.7 2609.05   680.9  2614.4   759.8  2619.2   784.7 2621.39
   798.6 2622.98   807.6 2624.65   838.7 2633.84   847.7 2636.05   913.7 2647.02
#Mann= 3 ,-1 , 0
       0     .05       0   493.6    .045       0   508.4     .05       0
#XS Ineff= 2 , 0
          274.92 2608.96
Permanent Ineff=
       F       F
Bank Sta=493.6,508.4
XS Rating Curve= 0 ,0
Exp/Cntr=0.3,0.1

Type RM Length L Ch R = 1 ,805     ,149.3,149.6,149.7
XS GIS Cut Line= 3
2417129.97587259538528.5048725862416923.77537202538188.730741763
      2416833.92      537712.032
#Sta/Elev= 30
       0 2617.01    29.7 2613.17    72.1 2610.19    85.1 2609.53    98.7 2609.59
   114.2 2608.13   146.2 2607.89   217.1 2604.31   282.6 2602.37     403 2603.38
   415.6 2602.79   427.8 2603.04     465 2602.34   472.6 2600.41   478.7 2600.91
   483.7 2602.21   488.9  2603.4   501.1 2604.47   525.5  2609.1   558.1 2617.82
   590.6 2628.07   606.9 2631.84   664.3 2642.84     672  2643.8   696.5 2645.07
   790.1 2647.95     843 2650.49   851.1 2651.42   867.4 2654.64   882.5 2655.22
#Mann= 6 ,-1 , 0
       0      .1       0   25.96     .05       0     465    .045       0
   483.7     .05       0  529.86      .1       0  822.58     .05       0
Bank Sta=465,483.7
XS Rating Curve= 0 ,0
Exp/Cntr=0.3,0.1

Type RM Length L Ch R = 1 ,656     ,116.2,113.5,110.8
XS GIS Cut Line= 3
2417211.34199318538478.2906268462417089.28883262538305.206694635
2417011.52225305537839.776883757
#Sta/Elev= 30
       0 2645.09     8.6 2641.91    14.9 2640.71    21.9  2640.5    25.8 2639.55
    45.9 2633.48    91.3 2622.29   103.3 2618.69   112.1 2618.18   121.6 2615.37
   146.1 2609.96   160.7 2607.97     195 2605.32   214.1 2605.14   258.7  2600.9
   408.8  2599.5   416.9 2597.64     421  2597.4   429.1 2597.81   434.9 2599.68
   457.5  2609.6   473.7 2617.82   485.9 2622.68   502.1 2628.08   530.5 2636.37
   542.6 2640.91   587.2 2652.44   623.7 2660.22   664.3 2666.91   683.7 2667.92
#Mann= 5 ,-1 , 0
       0      .1       0  189.77     .05       0  387.13      .1       0
   408.8    .045       0   434.9      .1       0
Bank Sta=408.8,434.9
XS Rating Curve= 0 ,0
Exp/Cntr=0.3,0.1

Type RM Length L Ch R = 1 ,542     ,124.5,123.9,123.3
XS GIS Cut Line= 2
2417325.96025596538448.1598725862417058.63382204537828.405125725
#Sta/Elev= 30
       0 2691.21    49.3    2690    91.7 2684.44   153.9 2673.83   162.6 2671.33
   193.1  2660.5   197.4 2658.58   207.3  2652.6   219.2 2650.17   240.4 2640.74
   265.2 2627.46   297.6  2608.6   313.8  2601.8   323.7 2599.35   336.8  2597.3
   384.7 2597.74   394.6 2596.69   402.2 2595.03   415.2  2596.4   423.9 2598.04
   432.7 2596.65   441.4 2596.43   482.8 2597.27   502.4 2599.28   517.8 2601.95
   563.6 2616.54     620 2639.35   645.6 2648.84   659.2 2652.59     675 2655.21
#Mann= 4 ,-1 , 0
       0      .1       0   71.41      .1       0   394.6    .045       0
   415.2      .1       0
Bank Sta=394.6,415.2
XS Rating Curve= 0 ,0
Exp/Cntr=0.3,0.1

Type RM Length L Ch R = 1 ,418     ,123.7,123.7,123.3
XS GIS Cut Line= 3
     2417461.549      538392.0182417203.21760273537875.516694714
2417058.39165218   537806.420465
#Sta/Elev= 30
       0 2708.34    41.5 2691.31    59.4 2684.81   119.2 2665.93   162.3 2650.23
   193.6 2639.89   202.5 2635.72   211.5 2634.54   247.4 2621.86   291.5 2605.36
   300.9 2602.33   318.9 2598.38   333.9 2596.46   354.7 2595.15   396.5 2594.47
   408.3 2592.72   417.3 2594.26   426.3 2594.97   453.4  2594.3   533.5 2593.96
   560.3 2595.24   575.3 2597.14   595.8 2602.29   604.6 2605.21   648.9 2617.28
     680  2629.8   698.3 2638.74   710.3 2643.75   719.8 2647.31     738 2652.88
#Mann= 4 ,-1 , 0
       0      .1       0  129.36      .1       0   396.5    .045       0
   417.3      .1       0
Bank Sta=396.5,417.3
XS Rating Curve= 0 ,0
Exp/Cntr=0.3,0.1

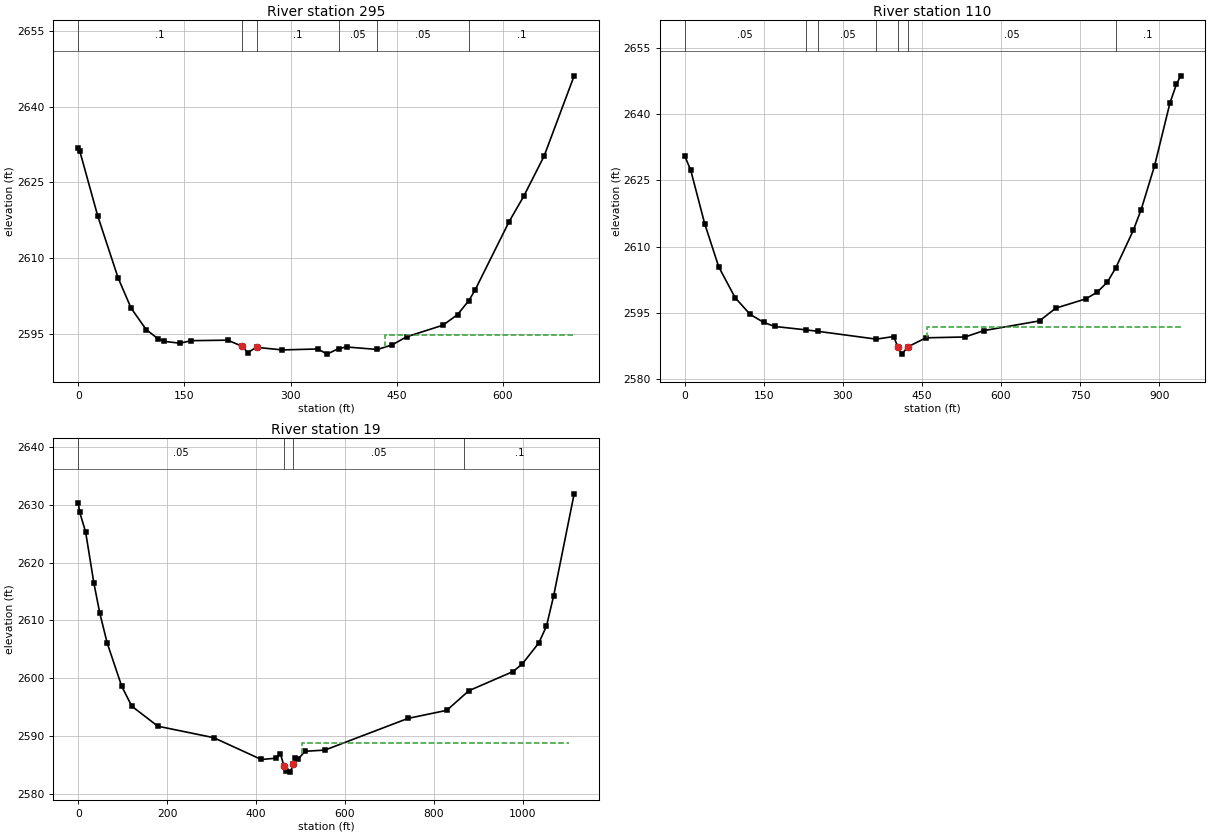
Type RM Length L Ch R = 1 ,295     ,184.4,185.1,183
XS GIS Cut Line= 4
2417386.96561387538196.8354640232417437.33106588538062.239569587
2417269.72333401537752.2323973212417069.16322762537792.344418597
#Sta/Elev= 30
       0 2631.88     2.1 2631.27    27.7 2618.32    56.4 2606.12    74.7 2600.16
      96 2595.92   113.1 2594.06   121.7 2593.58   143.7 2593.22   159.9 2593.72
   211.2 2593.82   230.82592.663   239.6 2591.38   251.9  2592.4   288.5 2591.89
   338.5 2592.08   351.7 2591.06   367.8 2592.16   379.4 2592.47   422.8 2591.98
   443.5 2592.89   463.9 2594.48   515.5 2596.79   535.9 2598.87   551.9 2601.64
   560.4 2603.65   608.7 2617.23   629.7 2622.34   658.3 2630.24   700.7 2646.09
#Mann= 6 ,-1 , 0
       0      .1       0   230.8    .045       0   251.9      .1       0
   367.8     .05       0   422.8     .05       0   551.9      .1       0
#XS Ineff= 2 , 0
                          433.98         2594.82
Permanent Ineff=
       F       F
Bank Sta=230.8,251.9
XS Rating Curve= 0 ,0
Exp/Cntr(USF)=0,0
Exp/Cntr=0.3,0.1

Type RM Length L Ch R = 1 ,110     ,92.3,90.5,89.3
XS GIS Cut Line= 4
2417406.90162574538201.1956787942417549.16674657537903.601099255
 2417379.9703706537682.8202625392417054.94358838537753.381843497
#Sta/Elev= 30
       0 2630.57    11.4 2627.34      38 2615.16    64.6 2605.38    95.7 2598.39
   124.1 2594.61   149.6  2592.8     171 2591.86   229.6  2591.1   253.6 2590.75
   363.5 2588.99   396.3 2589.58   404.62587.147     412 2585.59   423.42587.257
   457.6 2589.29   531.8 2589.48   567.6 2590.93     673 2593.13   703.6 2596.01
   760.4 2598.11     782  2599.6   801.6 2601.92   817.6 2605.16   850.8 2613.66
   865.7 2618.36   891.2 2628.32   920.3 2642.53   932.6 2646.78   940.6 2648.72
#Mann= 7 ,-1 , 0
       0     .05       0   229.6      .1       0   253.6     .05       0
   363.5     .05       0   404.6    .045       0   423.4     .05       0
   817.6      .1       0
#XS Ineff= 2 , 0
                          460.16         2591.81
Permanent Ineff=
       F       F
Bank Sta=404.6,423.4
XS Rating Curve= 0 ,0
Exp/Cntr(USF)=0,0
Exp/Cntr=0.3,0.1

Type RM Length L Ch R = 1 ,19      ,,,
XS GIS Cut Line= 4
 2417413.8039958538201.7109037292417609.46803855537826.369054444
 2417393.8782368537589.8003644082417034.01657385537686.509557465
#Sta/Elev= 30
       0 2630.42     3.2 2628.81    16.7 2625.32    35.4 2616.42    48.3 2611.36
    65.1 2606.12    97.9  2598.6   120.5 2595.15   179.1 2591.68   304.9 2589.69
     412 2585.91   444.7 2586.13     455  2586.9     463  2584.8   467.3 2583.94
   476.7 2583.72   484.3 2585.11   487.5  2586.1   495.6 2586.05   510.5 2587.33
   555.1 2587.54     742 2593.03   829.4 2594.43   879.1 2597.83   978.5 2601.15
   999.2 2602.46  1036.5 2606.11  1053.7 2609.02  1069.7 2614.21    1116 2631.95
#Mann= 4 ,-1 , 0
       0     .05       0     463    .045       0   484.3     .05       0
   869.1      .1       0
#XS Ineff= 1 ,-1
  504.13  1104.1 2588.85
Permanent Ineff=
       F
Bank Sta=463,484.3
XS Rating Curve= 0 ,0
Exp/Cntr(USF)=0,0
Exp/Cntr=0.3,0.1
LCMann Table=0

Chan Stop Cuts=-1
Use User Specified Reach Order=0
Composite Channel Slope=5